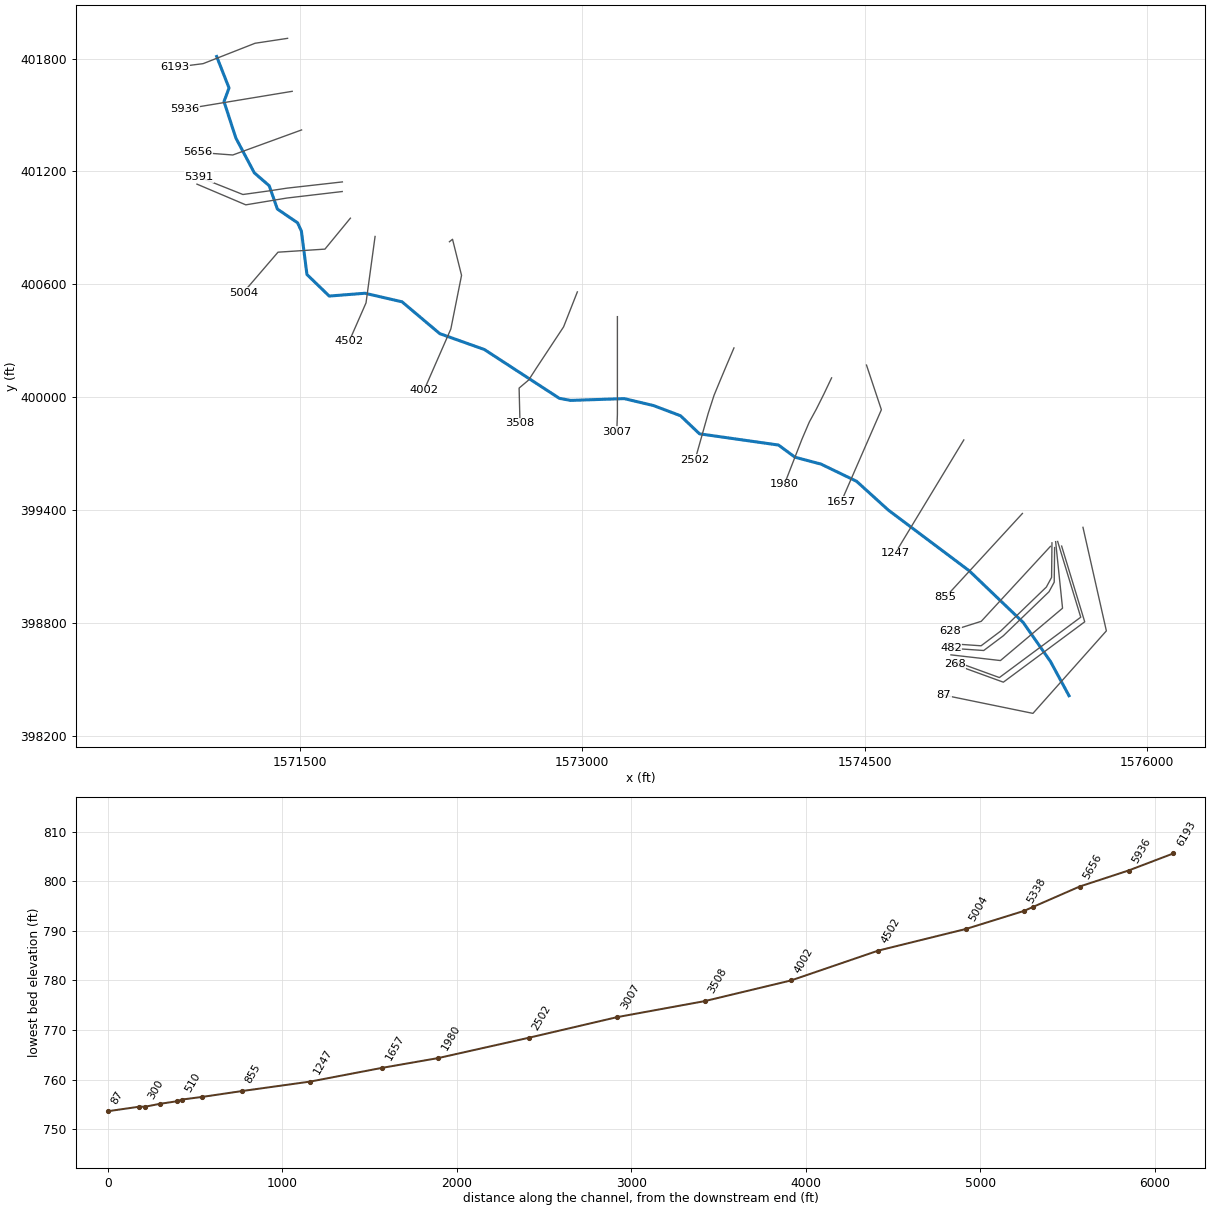
--- PADENFK.prj (project) ---

Proj Title=PADENFK
Current Plan=p01
Default Exp/Contr=0,0
English Units
Geom File=g01
Flow File=f01
Plan File=p01
BEGIN DESCRIPTION:
---------- MODELED AS PART OF WVEMD CTP PROGRAM, 2023----------
Stream Name: Paden Fork
Flood Zone:  AFH
Wetzel County, WV
HEC-RAS Version: RAS 6.3
Vertical Datum: NAVD88
Projection: NAD 1983 StatePlane West Virginia S FIPS 4702 (US Feet)
Terrain: 1-meter West Virginia FEMA R3 South Central (collected 2018-2020)
Land Use: 2019 NLCD
Hydrologic Method:
WV 2010 Regional Regression Equations
Additional Model Notes:
None
END DESCRIPTION:
DSS Export Rating Curves= 0
DSS Export Rating Curve Sorted= 0
DSS Export Volume Flow Curves= 0
DXF OffsetX= 0
DXF OffsetY= 0
DXF ScaleX= 0
DXF ScaleY= 0

--- PADENFK.p01 (plan) ---

Plan Title=Floodplain
Program Version=6.30
Short Identifier=Floodplain
Geom File=g01
Flow File=f01
Subcritical Flow
K Sum by GR= 0
Std Step Tol= 0.01
Critical Tol= 0.01
Num of Std Step Trials= 20
Max Error Tol= 0.3
Flow Tol Ratio= 0.001
Split Flow NTrial= 30
Split Flow Tol= 0.02
Split Flow Ratio= 0.02
Log Output Level= 0
Friction Slope Method= 1
Unsteady Friction Slope Method= 2
Unsteady Bridges Friction Slope Method= 1
Parabolic Critical Depth
Global Vel Dist= 0 , 0 , 0
Global Log Level= 0
CheckData=True
Encroach Param=-1 ,0,0, 0
Mapping Interval=1HOUR
Computation Time Step Use Courant=        0
Computation Time Step Use Time Series=    0
Computation Time Step Count To Double=0
Computation Time Step Max Doubling=0
Computation Time Step Max Halving=0
Computation Time Step Residence Courant=0
Run HTab= 0
Run UNet= 0
Run Sediment= 0
Run PostProcess= 0
Run WQNet= 0
Run RASMapper= 0
UNET Theta= 0
UNET Theta Warmup= 0
UNET ZTol= 0
UNET ZSATol= 0
UNET MxIter= 0
UNET Max Iter WO Improvement= 0
UNET MaxInSteps= 0
UNET DtIC= 0
UNET DtMin= 0
UNET MaxCRTS= 0
UNET WFStab= 0
UNET SFStab= 0
UNET WFX= 1
UNET SFX= 1
UNET Gravity=32.17405
UNET 1D Methodology=Finite Difference
UNET DSS MLevel= 1
UNET Pardiso=0
UNET DZMax Abort= 0
UNET Use Existing IB Tables= 0
UNET Froude Reduction=False
UNET Froude Limit= 0
UNET Froude Power= 0
UNET D1 Cores= 0
UNET WindReference=Eulerian
UNET WindDragFormulation=Hsu (1988)
UNET D2 Coriolis=0
UNET D2 Cores= 0
UNET D2 Theta= 1
UNET D2 Theta Warmup= 1
UNET D2 Z Tol= 0.01
UNET D2 Volume Tol= 0.01
UNET D2 Max Iterations= 20
UNET D2 Equation= 0
UNET D2 RampUpFraction=0.1
UNET D2 TimeSlices= 1
UNET D2 Turbulence Formulation=Non-Conservative (original)
UNET D2 Eddy Viscosity=0.3
UNET D2 Transverse Eddy Viscosity=0.1
UNET D2 Smagorinsky Mixing=0
UNET D2 BCVolumeCheck=0
UNET D2 Cores=0
UNET D2 SolverType=PARDISO (Direct)
UNET D2 Minimum Iterations= 3
UNET D2 Maximum Iterations= 30
UNET D2 Restart Number= 10
UNET D2 Relaxation Coeff=1.3
UNET D2 SOR Precondition Iterations= 10
UNET D2 ILUT Maximum Fill= 8
UNET D2 ILUT Tolerance=1E-08
UNET D2 Convergence Tolerance=0.00001
UNET D1D2 MaxIter= 0
UNET D1D2 ZTol=0.01
UNET D1D2 QTol=0.1
UNET D1D2 MinQTol=1
Write IC File= 0
Write IC File at Fixed DateTime=0
Write IC File at Sim End=0
Echo Input=False
Echo Parameters=False
Echo Output=False
Write Detailed= 0
HDF Write Warmup=0
HDF Write Time Slices=0
HDF Flush=0
HDF Compression= 1
HDF Chunk Size= 1
HDF Spatial Parts= 1
HDF Use Max Rows=0
HDF Fixed Rows= 1
Calibration Method= 0
Calibration Iterations= 20
Calibration Max Change=0.05
Calibration Tolerance=0.2
Calibration Maximum=1.5
Calibration Minimum=0.5
Calibration Optimization Method= 1
WQ AD Non Conservative
WQ ULTIMATE=-1
WQ Max Comp Step=1HOUR
WQ Output Interval=15MIN
WQ Output Selected Increments= 0
WQ Output face flow=0
WQ Output face velocity=0
WQ Output face area=0
WQ Output face dispersion=0
WQ Output cell volume=0
WQ Output cell surface area=0
WQ Output cell continuity=0
WQ Output cumulative cell continuity=0
WQ Output face conc=0
WQ Output face dconc_dx=0
WQ Output face courant=0
WQ Output face peclet=0
WQ Output face adv mass=0
WQ Output face disp mass=0
WQ Output cell mass=0
WQ Output cell source sink temp=0
WQ Output nsm pathways=0
WQ Output nsm derived pathways=0
WQ Create Restart=0
WQ Fixed Restart=0
WQ System Summary=0
WQ Write To DSS=0
Sorting and Armoring Iterations= 10
XS Update Threshold= 0.02
Bed Roughness Predictor= 0
Hydraulics Update Threshold= 0.02
Energy Slope Method= 1
Volume Change Method= 1
Sediment Retention Method= 0
Sediment TS Multiplier= 1
Warm Up Method= 0
XS Weighting Method= 0
Number of US Weighted Cross Sections= 1
Number of DS Weighted Cross Sections= 1
Upstream XS Weight=0
Main XS Weight=1
Downstream XS Weight=0
Number of DS XS's Weighted with US Boundary= 1
Upstream Boundary Weight= 1
Weight of XSs Associated with US Boundary= 0
Number of US XS's Weighted with DS Boundary= 1
Downstream Boundary Weight= 0.5
Weight of XSs Associated with DS Boundary= 0.5
Percentile Method= 0
Sediment Output Level= 3
Mass or Volume Output= 0
Output Increment Type= 1
Profile and TS Output Increment= 1
Transport Output Increment 1
XS Output Flag= 0
XS Output Increment= 10
Read HDF5 Sediment Hotstart= 0
Sediment Hotstart Type= 0
Write Gradation File= 0
Read Gradation Hotstart= 0
Write HDF5 File= 1
Write Binary Output= 1
Write DSS Sediment File= 0
DSS Sediment Output Type= 1
SV Curve= 0
Specific Gage Flag= 0
Subcell Erosion Methods= 0
Subcell Deposition Methods= 0
Advection Scheme= 1
Matrix Solver= 0
Implicit Weighting Factor= 1
Maximum Outer Loop Convergence Iterations= 5
Convergence Maximum Absolute= 0.001
Convergence RMSE= 0.0001
Grain Fractions Max Abs Error= 0.001
Max Subgrid Regions= 1
Max Subgrid Length Scale= 3.402823E+38
Initial Layer Thickness= 3.402823E+38
Min Layer Thickness= 3.402823E+38
Max Layer Thickness= 3.402823E+38
Number of Layers= 5

--- PADENFK.f01 (steady flow) ---

Flow Title=Flow
Program Version=6.31
Number of Profiles= 1
Profile Names=F01pct
River Rch & RM=PADENFK,Main,6193
     883
River Rch & RM=PADENFK,Main,3508
    1000
Boundary for River Rch & Prof#=PADENFK,Main            , 1
Up Type= 0
Dn Type= 3
Dn Slope=0.00614
DSS Import GetInterval= 0
DSS Import GetPeak= 0
DSS Import FillOption= 0

--- PADENFK.g01 (geometry) ---

Geom Title=Geometry
Program Version=6.30

River Reach=PADENFK         ,Main
Reach XY= 30
     1571057.059      401810.932     1571122.757      401643.631
     1571096.019       401571.44     1571159.043      401377.784
     1571257.208      401192.531     1571336.275      401124.159
     1571379.819       401000.02     1571487.151      400927.065
     1571507.396      400882.757     1571536.807      400652.432
     1571655.216      400537.842     1571845.435      400552.739
     1572042.147      400507.285     1572242.679      400338.075
     1572479.879       400253.66     1572878.268      399994.306
     1572937.473      399983.229     1573222.801      399992.778
     1573377.879       399956.11      1573521.88       399901.87
       1573623.1      399805.615      1574042.88      399746.029
1574130.66045594399681.254303016     1574268.622      399644.808
     1574457.694      399553.518     1574626.141      399400.732
     1575056.616       399077.59      1575343.09      398803.339
     1575488.618      398595.168     1575586.641      398413.974

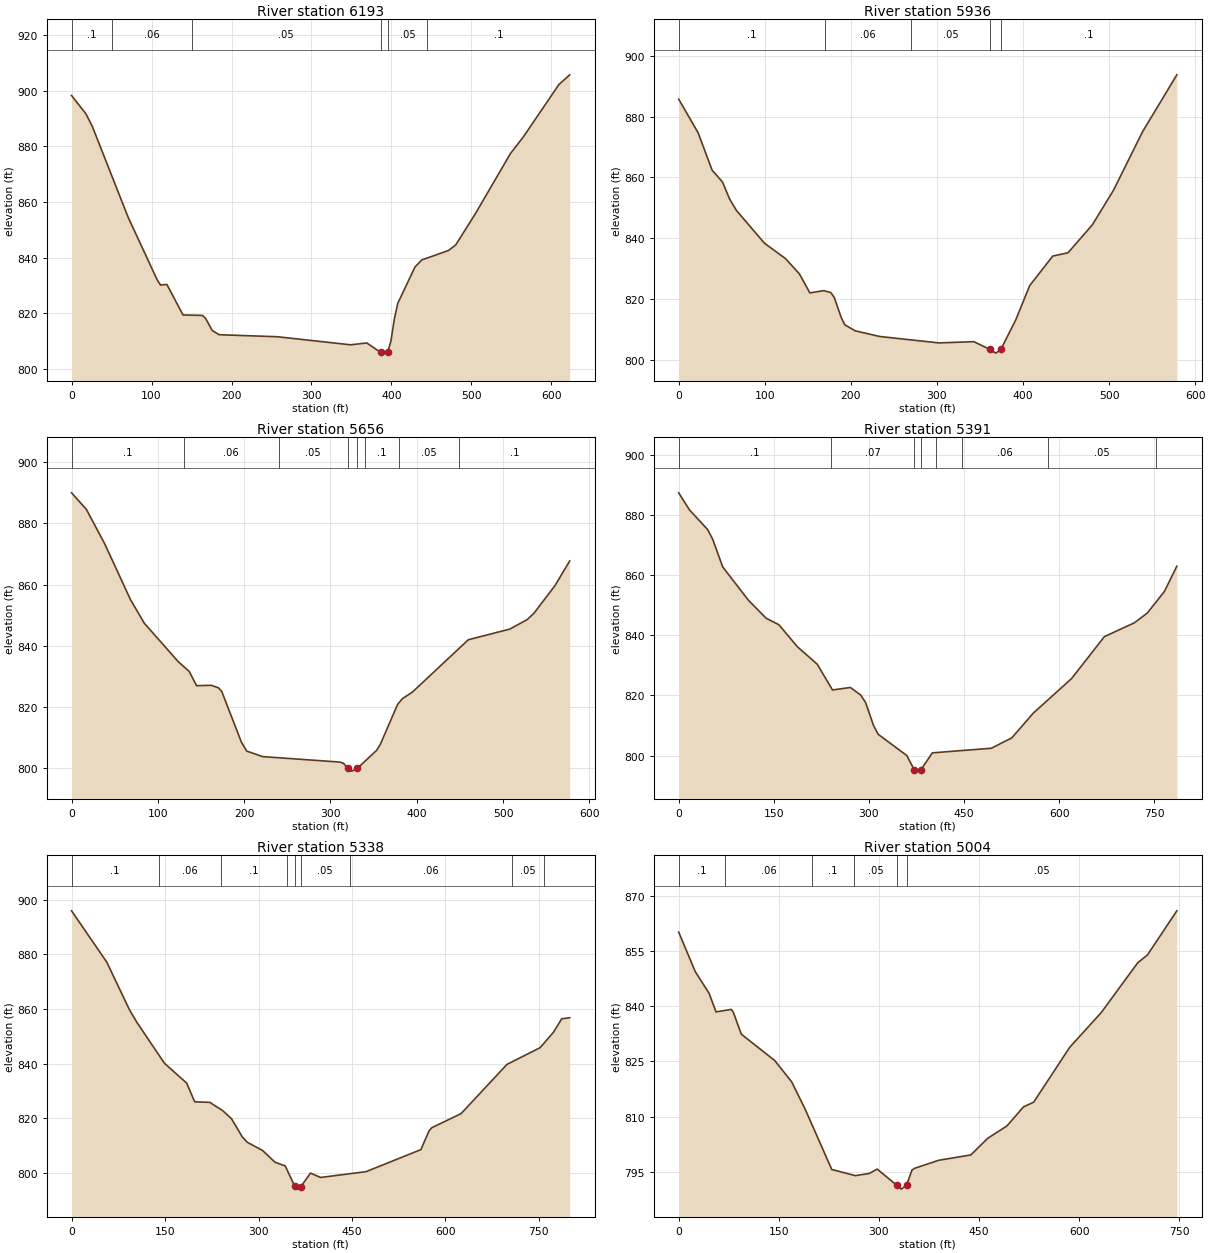
Type RM Length L Ch R = 1 ,6193    ,257.5,257.4,255.4
XS GIS Cut Line= 4
1571433.95376104401907.4627088081571260.99602598401881.256991375
1570984.96246903401772.9400259871570834.71635574401753.722499869
#Sta/Elev= 30
       0  898.28      18  891.68    26.1  887.07    70.6  854.58     107  832.02
   111.1  830.14   119.2  830.31   139.4  819.34   163.7  819.19   167.7  818.06
   175.9  813.77   184.5  812.24   257.5  811.51     349  808.61   369.2  809.28
   386.4   805.9   390.7  805.62  395.15 805.895   399.3  809.87   403.6  817.87
   407.9  823.52   429.4   836.6     438  839.14   471.5  842.56   480.4  844.56
   504.6  855.59   548.9  877.45   565.1  883.46   609.4  902.23   622.9  905.72
#Mann= 6 ,-1,0
       0      .1       0      50     .06       0     150     .05       0
   386.4    .045       0  395.15     .05       0  444.93      .1       0
Bank Sta=386.4,395.15
XS Rating Curve= 0 ,0
Exp/Cntr(USF)=0,0
Exp/Cntr=0.3,0.1

Type RM Length L Ch R = 1 ,5936    ,279.3,280.1,281.7
XS GIS Cut Line= 2
1571458.43006407 401625.875718241570887.35651804401531.520652815
#Sta/Elev= 30
       0   885.7    22.6  874.62    38.8  862.37      51  858.41    59.1  852.87
    67.2  849.06    99.6  838.34     124  833.29   140.2  828.25   152.4  821.98
   168.6  822.72   176.7  822.09   180.7   820.5   188.8  813.92   192.9  811.51
   205.1   809.5   233.4  807.65   302.4  805.53   342.9  805.94  361.72  803.38
   368.5  802.17  374.27  803.38   391.6  813.08   407.8  824.37   434.6  834.09
   452.4  835.19   480.7   844.4   505.1   855.7     539     875   578.8  893.71
#Mann= 5 ,-1,0
       0      .1       0     170     .06       0     270     .05       0
  361.72    .045       0  374.27      .1       0
Bank Sta=361.72,374.27
XS Rating Curve= 0 ,0
Exp/Cntr(USF)=0,0
Exp/Cntr=0.3,0.1

Type RM Length L Ch R = 1 ,5656    ,265.1,264.5,264.1
BEGIN DESCRIPTION:
Structure XS 4
END DESCRIPTION:
XS GIS Cut Line= 3
1571508.25306356401420.6180804521571142.68802136401287.511960722
1570954.99143383401301.659944708
#Sta/Elev= 30
       0  890.03    17.2   884.6    38.5  873.29    68.3  855.06    84.4  847.31
   123.6  834.78   136.4  831.55   144.9  826.91   161.9  827.03   170.4  826.19
   174.2  824.91   196.8  808.45     203  805.49   221.5  803.69   310.9   801.9
   315.2  801.49  319.94  799.82   324.7  798.94     331  799.81   353.5  805.72
   357.7  807.63   377.8  820.73   383.3  822.63   395.1  824.83   459.8  841.94
   507.9  845.43     528  848.53     536  850.66   560.3  859.69   577.3  867.74
#Mann= 8 ,-1,0
       0      .1       0     130     .06       0     240     .05       0
  319.94    .045       0     331     .05       0     340      .1       0
     380     .05       0  449.04      .1       0
Bank Sta=319.94,331
XS Rating Curve= 0 ,0
Exp/Cntr(USF)=0,0
Exp/Cntr=0.3,0.1

Type RM Length L Ch R = 1 ,5391    ,53,53.5,53.2
BEGIN DESCRIPTION:
Structure XS 3
END DESCRIPTION:
XS GIS Cut Line= 5
1571725.09820329401144.429863737 1571431.0700537401111.318245821
1571331.84023843401096.2526097511571196.53113607401077.522242317
1570961.88371636401170.853916509
#Sta/Elev= 30
       0  887.33    17.1  881.63    45.3  875.21    53.3  872.06    69.4  862.71
   109.7   851.7   137.8  845.68     158   843.5   187.2  836.18   218.4   830.4
   242.5  821.84   270.7  822.66     287  820.15   294.8  817.61     307  810.12
   314.4  807.13   359.6  800.06 371.768795.1747   375.7  794.87  381.27795.1753
     400  800.94   492.9  802.47   525.2  805.92   559.1  814.14   619.4  825.62
   671.2  839.56   718.4  844.14   738.8  847.39   765.8  854.55   785.4  862.95
#Mann= 8 ,-1,0
       0      .1       0     240     .07       0 371.768    .045       0
  381.27     .07       0  406.25     .05       0  446.25     .06       0
  582.85     .05       0  752.85      .1       0
Bank Sta=371.768,381.27
XS Rating Curve= 0 ,0
Exp/Cntr(USF)=0,0
Exp/Cntr=0.3,0.1

Type RM Length L Ch R = 1 ,5338    ,335.1,333.6,331.1
BEGIN DESCRIPTION:
Structure XS 2
END DESCRIPTION:
XS GIS Cut Line= 4
1571724.31203177401093.3287147431571430.28388217401058.737167732
1571211.72819879401022.573277674 1570952.2915962401132.637290892
#Sta/Elev= 30
       0  895.95    56.6  877.12    92.8  859.75   104.9  855.09   149.2  840.08
   184.7  832.87   197.6     826   221.7  825.82   242.3  822.82   256.7   819.8
   274.1  813.11   282.1  811.17   306.4   808.2   326.6  803.86   342.9  802.54
  358.32     795   363.1  794.03  368.17  794.99   383.3   799.9   399.6   798.3
   472.6  800.43   560.6   808.5   573.7  815.37     578  816.51     625  821.67
   698.8  839.72   751.8  845.81   773.5  851.53   786.6  856.42   799.4   856.8
#Mann= 9 ,-1,0
       0      .1       0     140     .06       0     240      .1       0
  346.06     .05       0  358.32    .045       0  368.17     .05       0
  446.06     .06       0  707.58     .05       0  757.58      .1       0
Bank Sta=358.32,368.17
XS Rating Curve= 0 ,0
Exp/Cntr(USF)=0,0
Exp/Cntr=0.3,0.1

Type RM Length L Ch R = 1 ,5004    ,491.4,502.1,511.9
BEGIN DESCRIPTION:
Structure XS 1
END DESCRIPTION:
XS GIS Cut Line= 6
1571767.64822163400951.7129894161571632.47929444400787.274515005
 1571557.6395491400782.3781993411571457.85267519400775.849997165
1571383.01260177400770.953681501 1571198.2934667400556.003252352
#Sta/Elev= 30
       0  860.08    24.8  849.38    45.5  843.49    55.9  838.44    78.7  839.13
    81.8  838.37    93.8   832.4   143.9  825.25   169.3  819.46   189.5  812.05
   229.3  795.71   264.7  794.04   285.4  794.63   297.4  795.82  326.44791.4579
   333.5  790.38   341.5   791.5   349.5  795.57   353.5  796.03   389.6  798.21
   437.7  799.65   462.9  804.16   491.9  807.54   516.4  812.66   531.9  813.98
   585.8  828.85     633  838.26   687.9  851.81   702.1  853.85   746.3  865.86
#Mann= 6 ,-1,0
       0      .1       0      70     .06       0     200      .1       0
  262.86     .05       0  326.44    .045       0   341.5     .05       0
Bank Sta=326.44,341.5
XS Rating Curve= 0 ,0
Exp/Cntr(USF)=0,0
Exp/Cntr=0.3,0.1

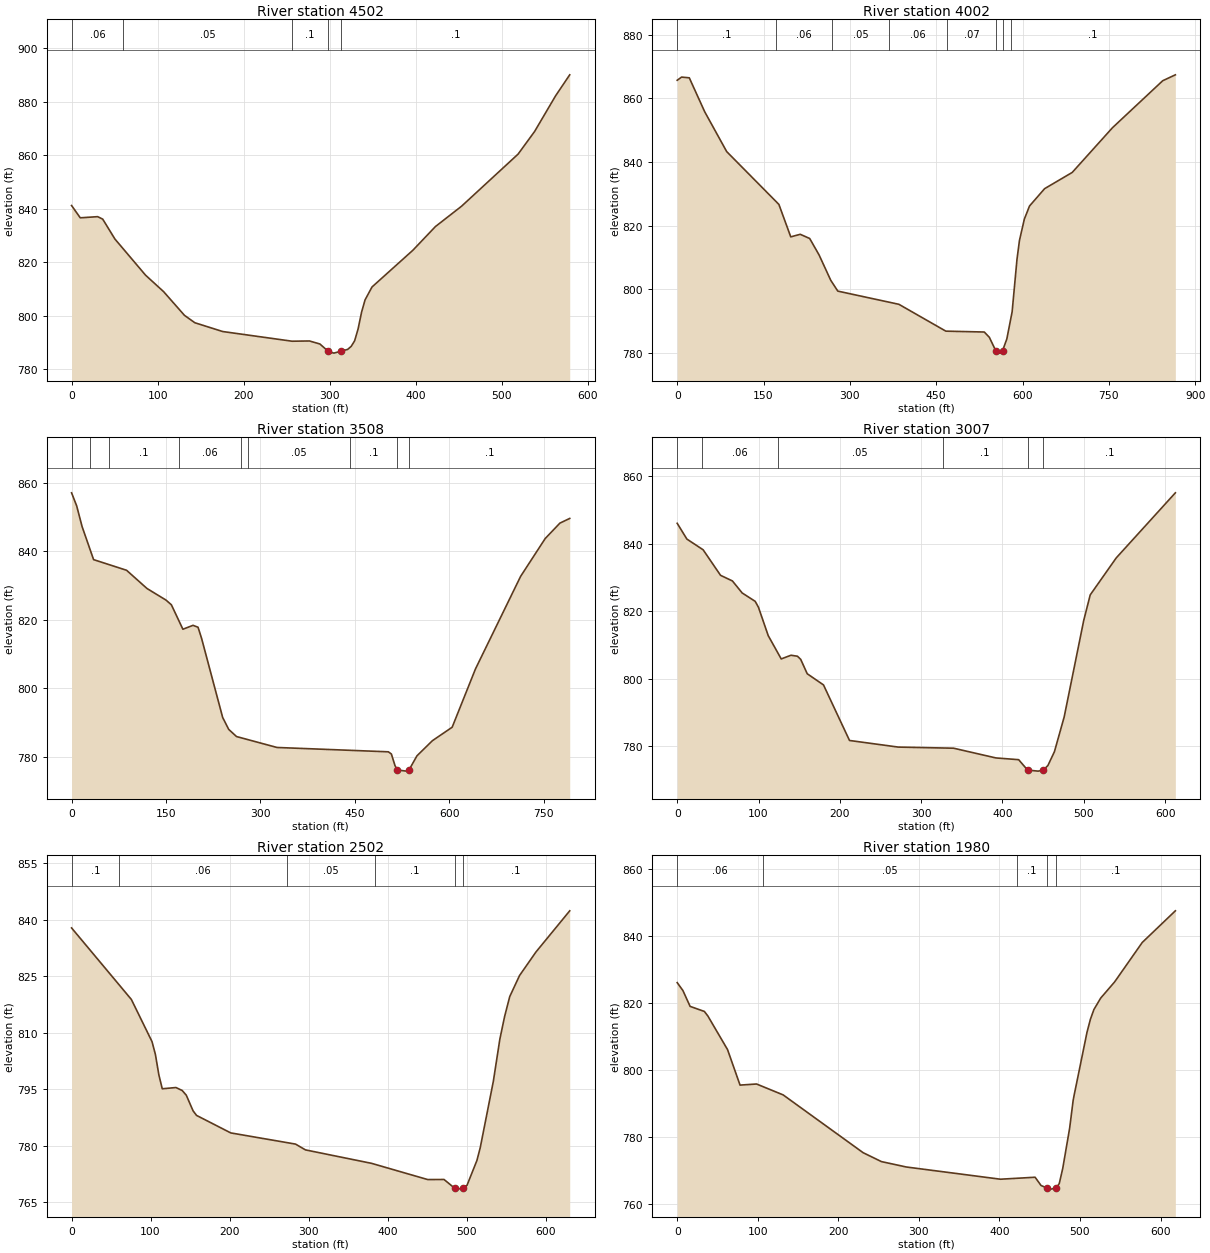
Type RM Length L Ch R = 1 ,4502    ,502.2,500,497.7
XS GIS Cut Line= 6
1571898.89412817400854.5332346711571886.22945534 400761.64267242
 1571874.4076286400674.9450111691571864.27444676400600.632495761
  1571850.763647400501.5493605881571761.31958434400297.564168694
#Sta/Elev= 30
       0  841.16    10.1  836.57    30.3     837    36.2  836.08    50.4  828.64
      86  815.14     107  808.98   131.2  800.14   143.3  797.37   175.6  794.09
   256.3  790.47   276.5  790.56   288.6  789.44   298.2786.7273   304.8  786.02
   312.9  786.72   320.9  787.41     325  788.54     329  790.62     333  795.03
   337.1  801.35   341.1  805.89   349.2  810.73   396.7  824.45   422.9   833.3
   453.2  840.88     519  860.37   538.2  868.83   562.6  882.16     579  889.99
#Mann= 5 ,-1,0
       0     .06       0      60     .05       0  256.25      .1       0
   298.2    .045       0   312.9      .1       0
Bank Sta=298.2,312.9
XS Rating Curve= 0 ,0
Exp/Cntr(USF)=0,0
Exp/Cntr=0.3,0.1

Type RM Length L Ch R = 1 ,4002    ,495.6,494.6,493
XS GIS Cut Line= 6
 1572294.1565483400826.5086020361572310.51219381400839.626630952
1572358.44217539400647.9067046041572301.48945159400362.742879674
1572261.40751076400271.1269211771572158.69839859400036.361314595
#Sta/Elev= 30
       0  865.68     7.6  866.68      21  866.45    47.9  855.75      86  843.28
   176.7   826.7   197.3  816.51   213.8  817.31   230.2     816   246.5  810.84
   266.9  802.84   279.1  799.47   385.2  795.33   466.8   786.9   533.6  786.63
   542.4  784.96  553.53780.7634   559.8     780   565.3  780.72   572.8  784.47
     582  793.01   590.4  809.43   594.7  815.37   603.2  822.08   612.2   826.2
   638.4  831.64   686.4  836.74   756.3  850.77   843.6  865.53   865.6  867.39
#Mann= 8 ,-1,0
       0      .1       0  170.97     .06       0  268.59     .05       0
  368.59     .06       0  468.59     .07       0  553.53    .045       0
   565.3     .07       0  579.38      .1       0
Bank Sta=553.53,565.3
XS Rating Curve= 0 ,0
Exp/Cntr(USF)=0,0
Exp/Cntr=0.3,0.1

Type RM Length L Ch R = 1 ,3508    ,496.2,500.6,506.8
XS GIS Cut Line= 6
1572973.91755079400560.1072379081572900.68774508400374.033308514
1572756.05220757400154.9743634241572715.42466416400091.925933085
1572664.35583991400048.7823413731572669.09123316399861.546012717
#Sta/Elev= 30
       0  857.11     8.1  853.31    16.7  847.26      35   837.6    87.4  834.49
   119.9  829.16     150  825.79   158.6  824.41   176.9  817.27     193  818.41
     201  817.85   206.6  814.61   240.1  791.51   249.7  788.02   262.1  785.93
   326.4  782.74   503.4  781.47   508.2  780.83     514  777.43   517.7  776.16
     532  775.83   536.2  776.18   548.9  780.31   573.4  784.72   604.8  788.65
   641.8  805.66   713.6  832.72   752.6  843.75     776  848.26   791.6  849.63
#Mann= 9 ,-1,0
       0      .1       0      30     .06       0      60      .1       0
     170     .06       0  269.97     .07       0  279.97     .05       0
  442.47      .1       0   517.7    .045       0   536.2      .1       0
Bank Sta=517.7,536.2
XS Rating Curve= 0 ,0
Exp/Cntr(USF)=0,0
Exp/Cntr=0.3,0.1

Type RM Length L Ch R = 1 ,3007    ,505.7,504.9,499.1
XS GIS Cut Line= 3
 1573186.6894241400428.439062369 1573186.6894241399909.689115626
1573183.41843327399815.938975048
#Sta/Elev= 30
       0  846.03    11.9  841.36    31.9  838.18    53.3  830.62    67.9  828.95
    79.9  825.39    95.9  822.91    99.9  821.17   111.9  812.77   127.9  805.85
   139.9  806.94   147.9  806.65   151.9  805.71   159.9  801.46   179.9  798.15
   211.9  781.69   271.9  779.73   339.9   779.4   391.9  776.52   419.9     776
  430.94 772.912   443.9  772.61  450.16772.9152   455.9  774.29   463.9  778.37
   475.9  788.68   499.9  817.23   507.9  824.82   539.9  835.78   612.6  855.06
#Mann= 6 ,-1,0
       0      .1       0      30     .06       0  123.75     .05       0
  326.25      .1       0  430.94    .045       0  450.16      .1       0
Bank Sta=430.94,450.16
XS Rating Curve= 0 ,0
Exp/Cntr(USF)=0,0
Exp/Cntr=0.3,0.1

Type RM Length L Ch R = 1 ,2502    ,522.4,522.3,521.2
XS GIS Cut Line= 6
1573806.16962209 400262.147751081573766.87737785400170.123328822
1573730.72029793400083.9971887341573700.31747159400010.380866157
1573669.16661526399914.0716755711573599.47810635399667.479649069
#Sta/Elev= 30
       0  837.83    75.7  818.83   101.8  807.65   106.1  804.26   110.5   798.8
   114.8  795.11   132.1  795.44     140  794.66   145.2  793.41   153.8  789.26
   158.2  788.04   201.5  783.39   283.5  780.42   296.1  778.88   379.7  775.31
   450.8     771   471.5  771.02   485.1  768.68   488.2  768.46  494.94768.6745
   500.6  769.48   513.1  776.06   517.3  779.44   533.9  797.08   542.2  808.34
   548.2  814.33   554.7  819.61   567.1  825.19   587.9  831.45   630.6  842.37
#Mann= 6 ,-1,0
       0      .1       0      60     .06       0  273.12     .05       0
  384.34      .1       0   485.1    .045       0  494.94      .1       0
Bank Sta=485.1,494.94
XS Rating Curve= 0 ,0
Exp/Cntr(USF)=0,0
Exp/Cntr=0.3,0.1

Type RM Length L Ch R = 1 ,1980    ,322.9,322.7,322.4
XS GIS Cut Line= 6
1574324.92415605400102.968734384 1574283.5886088 400016.10145405
1574243.32392555399935.7715622191574206.89552073399869.046958134
1574167.48877538399777.0779819641574074.49158606399538.298603878
#Sta/Elev= 30
       0     826     7.1  823.63      16  818.91    33.7   817.4    38.1  816.02
    62.5     806      78   795.4    98.5  795.73   131.5  792.48   230.8  775.22
   253.5  772.56   284.4  770.95   401.3   767.3   444.3  767.89   451.7  765.42
   458.7764.7112     464  764.34   470.6  764.72   474.3  766.01   478.6  770.52
   487.2  782.58   491.5  790.79   492.7  792.33   508.7  811.15     513   815.1
   517.3  817.97   525.7  821.38     543  826.21   577.3  837.99   618.4  847.44
#Mann= 5 ,-1,0
       0     .06       0   106.2     .05       0  422.13      .1       0
   458.7    .045       0   470.6      .1       0
Bank Sta=458.7,470.6
XS Rating Curve= 0 ,0
Exp/Cntr(USF)=0,0
Exp/Cntr=0.3,0.1

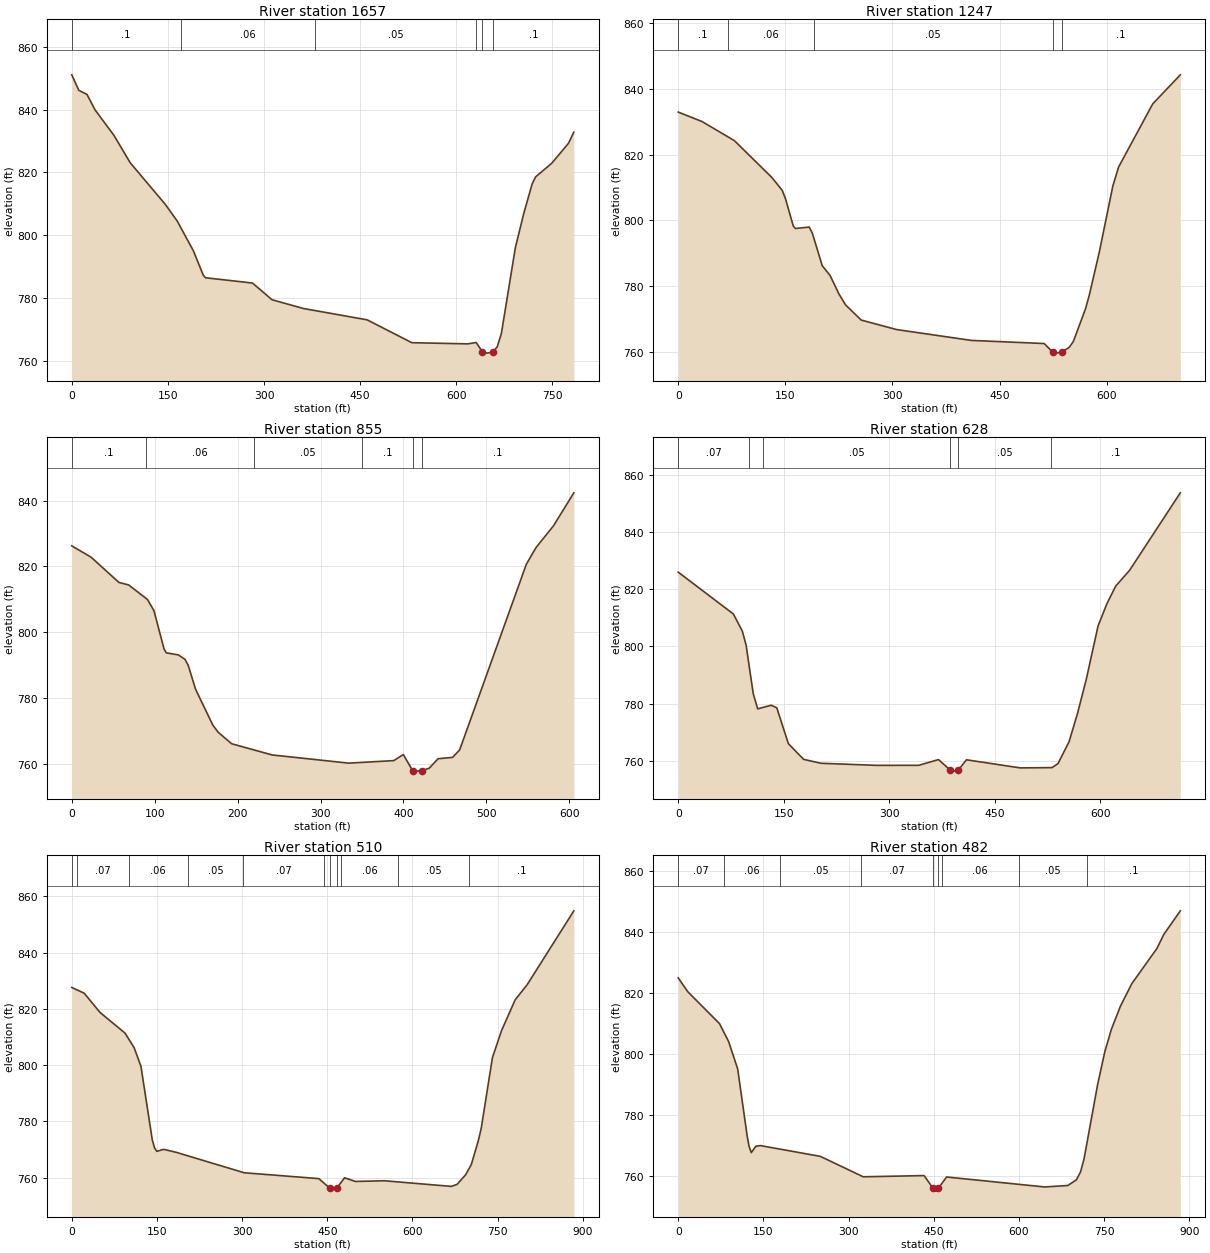
Type RM Length L Ch R = 1 ,1657    ,412.7,410.4,409.9
XS GIS Cut Line= 3
1574510.49834866400171.0033878121574589.58281827399933.749978955
1574376.29440021399444.864166766
#Sta/Elev= 30
       0  851.14      11  846.19    23.7   844.9    36.3  839.97    65.8  831.84
    91.1  823.12     146  809.81   164.5  804.52   189.8     795     205  787.32
   208.8   786.4     282  784.72   312.5  779.39   361.5   776.6   460.9  772.98
   530.7  765.69     618  765.31   631.1  765.75  640.67762.7995   648.5  762.36
   657.3  762.79   663.9  764.35   670.4   768.6   692.2  795.96   705.3  806.87
   718.4  816.32   723.9   818.6   748.9  822.91   775.1  829.28   783.5  832.85
#Mann= 6 ,-1,0
       0      .1       0     170     .06       0  380.09     .05       0
  630.09      .1       0  640.67    .045       0   657.3      .1       0
Bank Sta=640.67,657.3
XS Rating Curve= 0 ,0
Exp/Cntr(USF)=0,0
Exp/Cntr=0.3,0.1

Type RM Length L Ch R = 1 ,1247    ,392.2,391.1,389.8
XS GIS Cut Line= 2
1575027.60959445399773.0629076261574663.34173438399171.541638707
#Sta/Elev= 30
       0  833.01    33.3  830.14    78.7  824.31   131.1   813.1   145.6   809.2
   150.3  806.58   161.2  798.27   164.3  797.56   183.5  797.99   187.7  796.21
   201.7  786.22   212.6  783.28   225.1   777.6   234.4  774.29   256.3  769.67
   305.8  766.78   410.7  763.47   512.6  762.52   524.4   759.9     529   759.6
  537.04759.8767   547.7  761.38   553.4  763.15   570.5  773.15   575.8  777.33
   589.8  790.42   608.7   810.5   616.8   816.3   664.6  835.52   703.2  844.36
#Mann= 5 ,-1,0
       0      .1       0      70     .06       0     190     .05       0
   524.4    .045       0  537.04      .1       0
Bank Sta=524.4,537.04
XS Rating Curve= 0 ,0
Exp/Cntr(USF)=0,0
Exp/Cntr=0.3,0.1

Type RM Length L Ch R = 1 ,855     ,227.2,227.2,227.2
XS GIS Cut Line= 2
1575339.15447476399382.4335576911574929.35313219 398936.68472893
#Sta/Elev= 30
       0  826.22    23.3  822.77    56.9  815.09    68.6  814.33    91.3   809.9
    99.1  806.51   111.2  794.93   113.9  793.68   128.6  793.05   136.5   791.7
   140.4  789.91   149.3   782.6     170  771.75   176.4  769.55   192.8  766.02
   241.7  762.61     334  760.12   388.4  760.89   399.8  762.73   411.1  757.86
   415.5  757.69  422.35757.8648     431  758.57   441.8  761.46   459.3  761.88
   467.8  764.15   548.2  820.61     560  825.74     581  832.33   605.5  842.35
#Mann= 6 ,-1,0
       0      .1       0      90     .06       0     220     .05       0
     350      .1       0   411.1    .045       0  422.35      .1       0
Bank Sta=411.1,422.35
XS Rating Curve= 0 ,0
Exp/Cntr(USF)=0,0
Exp/Cntr=0.3,0.1

Type RM Length L Ch R = 1 ,628     ,118.3,117.9,117.7
BEGIN DESCRIPTION:
Structure XS 4
END DESCRIPTION:
XS GIS Cut Line= 3
1575487.91522324399207.516335008 1575120.3081441398809.214430175
1574956.60240707398757.325558169
#Sta/Elev= 30
       0  825.94    78.4  811.34    91.1  805.35    96.6  800.38     100  794.56
   106.7  783.47   112.9  778.25   132.2   779.5   140.1  778.61   156.5  766.12
   178.2  760.62   202.9  759.25   282.2  758.52   341.7  758.53     370  760.54
  386.46   756.9   394.9  756.51   398.3   756.9   409.6  760.47     486  757.64
   531.3  757.73   539.8  759.13   555.5  766.73   567.4  776.47     580  788.51
   596.8  807.18   609.6  815.05   621.9   821.1   641.5  826.54   713.7  853.62
#Mann= 6 ,-1,0
       0     .07       0     100     .06       0     120     .05       0
  386.46    .045       0   398.3     .05       0     530      .1       0
Bank Sta=386.46,398.3
XS Rating Curve= 0 ,0
Exp/Cntr(USF)=0,0
Exp/Cntr=0.3,0.1

Type RM Length L Ch R = 1 ,510     ,27.8,27.8,27.8
BEGIN DESCRIPTION:
Structure XS 3
END DESCRIPTION:
XS GIS Cut Line= 6
1575496.19344438399226.2859477381575494.11431443399042.458238571
1575466.42193849398991.4208635161575223.39584973398757.232027433
1575119.50816679398679.2204960961574945.08110066398691.213270091
#Sta/Elev= 30
       0   827.6    21.8  825.56    49.8  818.72    93.8  811.38   109.8  806.22
   121.8  799.63   141.8  773.46   145.8  770.62   149.8  769.39   161.8   770.1
   183.8  769.05   303.7  761.78   435.1   759.7   454.9  756.23   460.6  755.97
  466.33756.2313   480.4  759.99   499.7  758.69   550.6  758.94   668.5  756.94
   678.6  757.67   693.6  761.06   703.6  764.68   715.9  773.12   721.2  777.69
   740.8  802.65   756.8  812.23   780.9  823.22     802  828.57   884.2  854.81
#Mann= 11 ,-1,0
       0     .06       0      10     .07       0     100     .06       0
  203.84     .05       0  301.91     .07       0  444.41     .05       0
   454.9    .045       0  466.33     .05       0  474.41     .06       0
  574.41     .05       0  699.41      .1       0
Bank Sta=454.9,466.33
XS Rating Curve= 0 ,0
Exp/Cntr(USF)=0,0
Exp/Cntr=0.3,0.1

Type RM Length L Ch R = 1 ,482     ,99.8,99.4,99.2
BEGIN DESCRIPTION:
Structure XS 2
END DESCRIPTION:
XS GIS Cut Line= 6
 1575510.2338837399201.2099220371575508.15475376 399017.38221287
1575480.46237781398966.3448378151575237.43628906398732.156001732
1575133.54860612398654.1444703951574959.12153999 398666.13724439
#Sta/Elev= 30
       0  824.95    16.7  820.44    72.7  809.94    88.7  804.07   104.7  795.08
   121.4  773.08   124.7  769.68   128.7  767.61   136.7  769.71   144.7  769.92
   250.3  766.38   325.7  759.68     433  760.07  448.99755.8373   452.8  755.63
   457.8  755.85   472.6  759.61   645.4  756.34   686.1  756.82   701.1  758.65
   708.5  761.27   714.8  765.66   738.4  789.77   751.3  800.77   762.9  808.13
   778.9  815.72   798.7  823.04   843.1  834.63   855.1   839.2   884.2  846.96
#Mann= 9 ,-1,0
       0     .07       0      80     .06       0     180     .05       0
  321.91     .07       0  448.99    .045       0   457.8     .07       0
  464.41     .06       0  599.41     .05       0  719.32      .1       0
Bank Sta=448.99,457.8
XS Rating Curve= 0 ,0
Exp/Cntr(USF)=0,0
Exp/Cntr=0.3,0.1

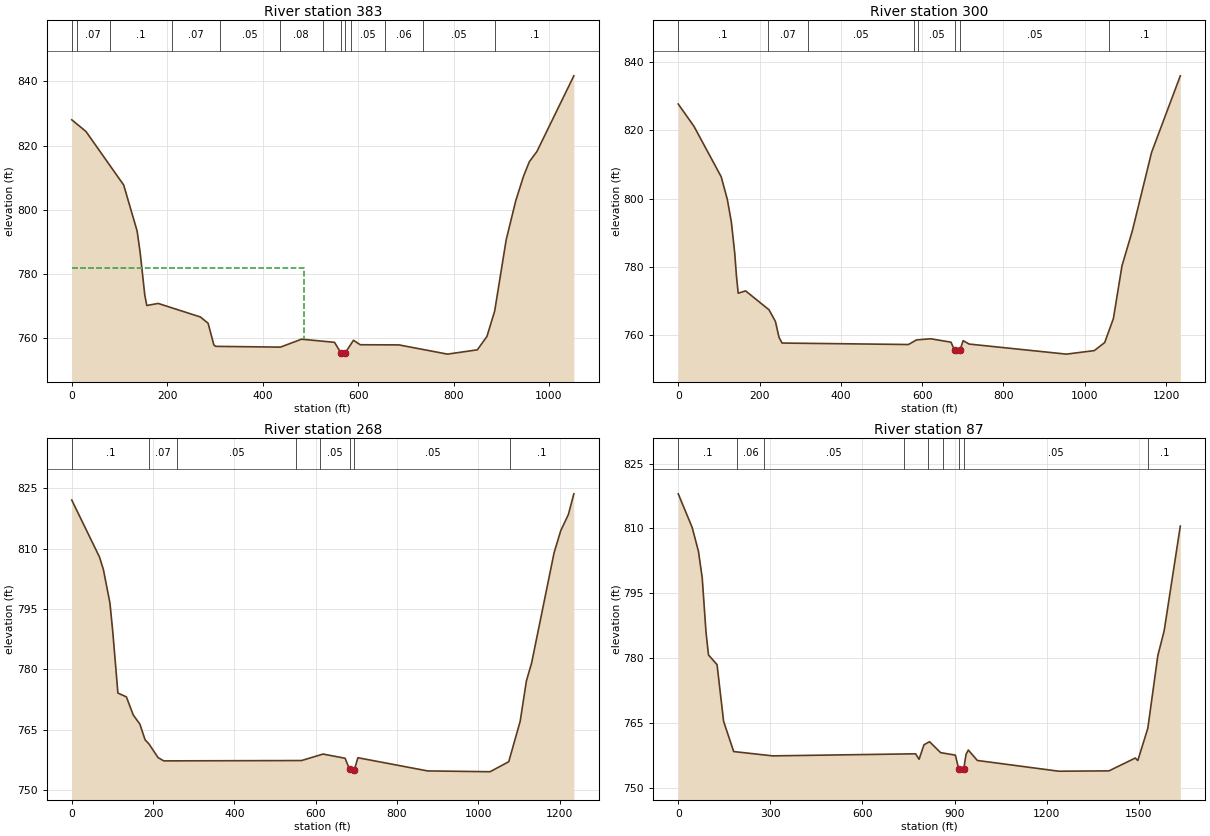
Type RM Length L Ch R = 1 ,383     ,83.2,83,82.7
BEGIN DESCRIPTION:
Structure XS 4 AND Structure XS 1
END DESCRIPTION:
XS GIS Cut Line= 4
1575515.69359039399232.709590284 1575552.3600263398878.986326171
1575222.36210308398600.7527830571574959.22650416398630.948671457
#Sta/Elev= 30
       0  828.04    29.7  824.42   108.8  807.74   136.9  793.47   143.3  786.74
     153  773.51   157.2  770.24   181.1  770.88   269.6  766.66   285.7  764.71
   297.8  757.95   301.8  757.52   437.3  757.28   481.5  759.75   550.6  758.77
   563.8755.5266   573.3  755.54   590.3  759.42   604.5  758.02   685.6  757.97
   787.3   755.1   849.9  756.44     870  760.61   886.2   768.5   910.3  790.67
   930.4  802.86   946.5  810.41   958.8  814.98   974.7  818.17  1052.1  841.73
#Mann= 13 ,-1,0
       0     .06       0      10     .07       0      80      .1       0
     210     .07       0     310     .05       0  435.62     .08       0
  525.62     .07       0   563.8    .045       0   573.3     .07       0
  585.62     .05       0  655.62     .06       0  735.62     .05       0
  887.26      .1       0
#XS Ineff= 2 , 0
          486.56  781.79
Permanent Ineff=
       F       F
Bank Sta=563.8,573.3
XS Rating Curve= 0 ,0
Exp/Cntr(USF)=0,0
Exp/Cntr=0.3,0.1

Type RM Length L Ch R = 1 ,300     ,32.3,32.3,32.3
BEGIN DESCRIPTION:
Structure XS 3
END DESCRIPTION:
XS GIS Cut Line= 4
1575526.43699802 399233.627223171575649.07975561398831.107403403
1575216.68541797398510.3494220261574957.24881538398604.690004784
#Sta/Elev= 30
       0  827.65    38.8  821.11   105.7  806.38   120.8  799.76   130.8  793.05
   139.1  783.95   143.2  777.42   147.5  772.34   165.7  773.02   223.4  767.49
   239.1  764.09   247.9  759.45   255.4  757.77   566.3  757.34   586.3  758.69
   621.2  759.02     671  758.02   680.2  755.64   686.4  754.69  692.98755.6225
   700.9  758.46   715.8  757.47   954.9  754.53  1023.6  755.56  1049.2  757.92
  1070.6  764.94  1091.7  780.35  1117.3  790.63  1164.5   813.5  1235.2  835.89
#Mann= 8 ,-1,0
       0      .1       0     220     .07       0     320     .05       0
  580.79     .08       0  590.79     .05       0   680.2    .045       0
  692.98     .05       0 1059.17      .1       0
Bank Sta=680.2,692.98
XS Rating Curve= 0 ,0
Exp/Cntr(USF)=0,0
Exp/Cntr=0.3,0.1

Type RM Length L Ch R = 1 ,268     ,179.4,181.3,183
BEGIN DESCRIPTION:
Structure XS 2
END DESCRIPTION:
XS GIS Cut Line= 4
1575547.57397799399209.1266014441575670.21673558398806.606781676
1575237.82239794398485.8488002991574978.38579535398580.189383057
#Sta/Elev= 30
       0  822.01    68.2  807.89    77.8  804.79    93.9  796.49     101  789.24
   113.5  774.15   134.4   773.2   151.2  768.72   167.6  766.44   180.4  762.56
     190  761.52   212.4  758.13   226.4  757.33   565.3  757.41   618.2  759.02
   672.5  757.98  683.36 755.232   692.4  754.54   695.4  755.19     704  758.11
   875.5  754.84  1029.1  754.64    1075  757.12  1103.1  767.12  1118.5  777.16
  1131.4  781.65  1186.6  808.95  1202.9   814.4  1221.7  818.42  1235.2  823.56
#Mann= 8 ,-1,0
       0      .1       0     190     .07       0     260     .05       0
  550.79     .06       0  610.79     .05       0  683.36    .045       0
   695.4     .05       0 1079.17      .1       0
Bank Sta=683.36,695.4
XS Rating Curve= 0 ,0
Exp/Cntr(USF)=0,0
Exp/Cntr=0.3,0.1

Type RM Length L Ch R = 1 ,87      ,,,
BEGIN DESCRIPTION:
Structure XS 1
END DESCRIPTION:
XS GIS Cut Line= 4
1575660.92676015399308.6839366531575785.33028965398758.490844638
1575394.99349375398320.0247077291574920.48667604398417.355155589
#Sta/Elev= 30
       0  818.01    45.3  810.26    65.8  804.73    78.1   798.6    90.4  786.06
    98.6  780.73   126.5  778.48   147.8  765.37   180.6  758.38   307.7  757.38
   773.2  757.86   784.5  756.59   800.5  759.95   818.6  760.66   854.7  758.13
   902.8  757.55  913.73   754.3   920.8  753.62  929.93   754.3   937.5  757.73
   944.9  758.73   974.3  756.32  1239.8  753.83  1403.1  753.91  1488.9  756.88
  1497.1   756.3  1529.7  763.79  1562.4  780.63  1582.8  786.28  1635.5  810.55
#Mann= 9 ,-1,0
       0      .1       0     190     .06       0     280     .05       0
  734.08     .06       0  814.08     .07       0  864.08     .05       0
  913.73    .045       0  929.93     .05       0 1531.12      .1       0
Bank Sta=913.73,929.93
XS Rating Curve= 0 ,0
Exp/Cntr(USF)=0,0
Exp/Cntr=0.3,0.1
LCMann Table=0

Chan Stop Cuts=-1
Use User Specified Reach Order=0
Composite Channel Slope=5